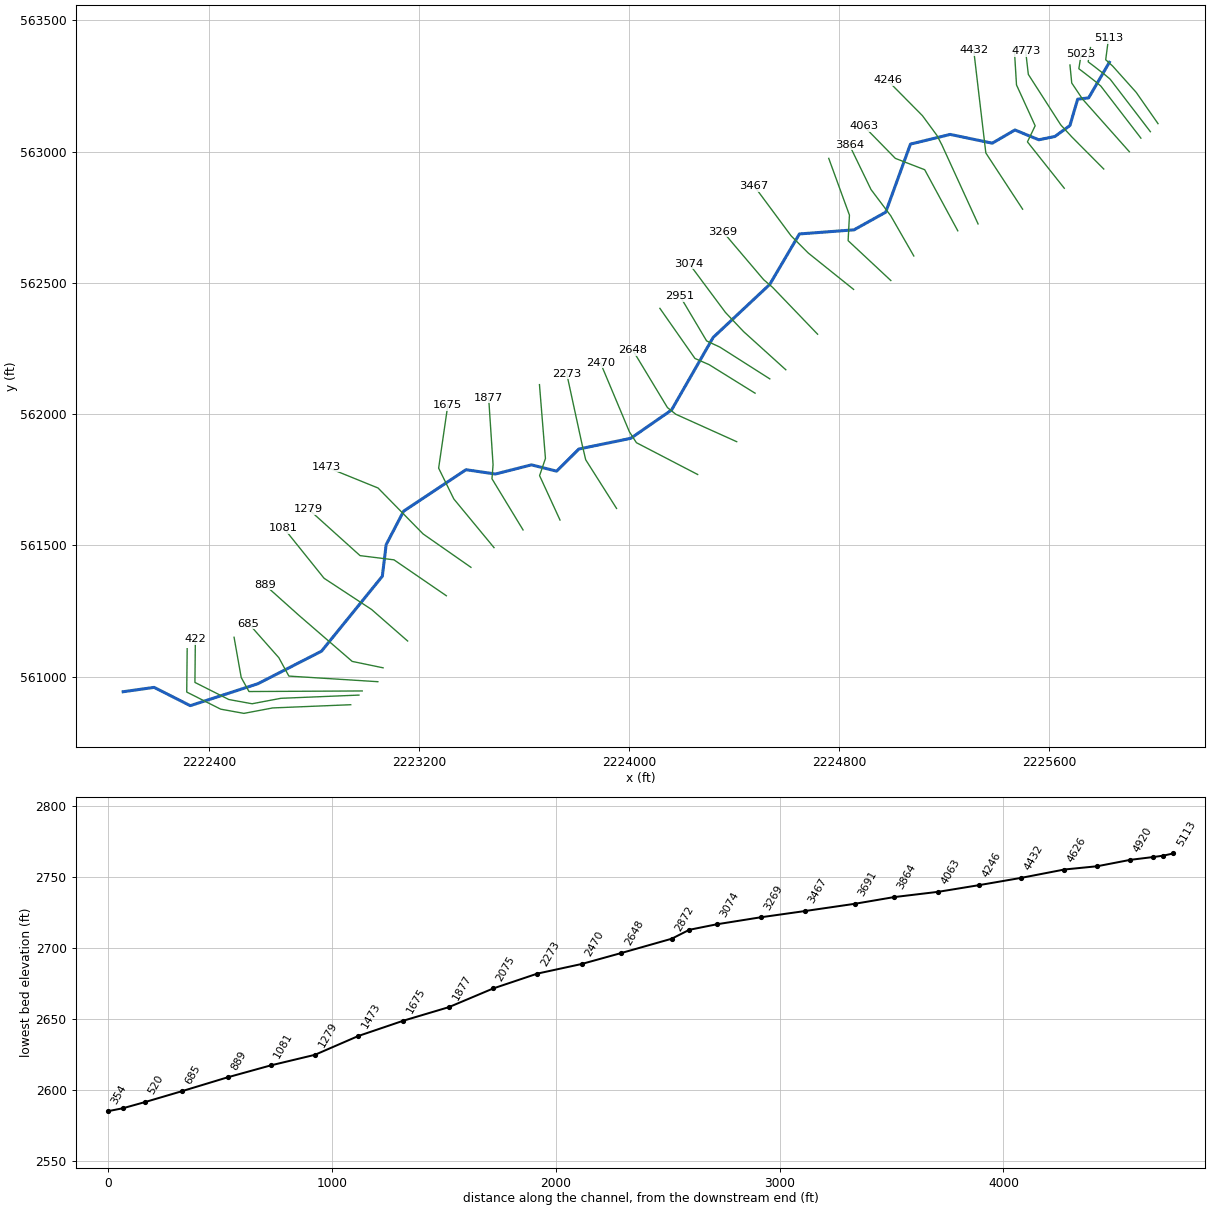
--- MUDLKRN.prj (project) ---

Proj Title=MUDLKRN
Current Plan=p01
Default Exp/Contr=0,0
English Units
Geom File=g01
Flow File=f01
Plan File=p01
BEGIN DESCRIPTION:
----------MODEL BY WOOD PLC 2022----------
AFH study
Randolph County, WV
HEC-RAS Version: RAS 6.2
Vertical Datum: NAVD88
Projection: NAD 1983 StatePlane West Virginia S FIPS 4702 (US Feet)
Terrain: 1-meter LIDAR (FEMA Region III 3DEP collected 2016-2018)
Land Use: 2019 NLCD
Hydrologic Method:
WV SIR2010-5033 regression equations
Additional Model Notes:
KWSE with VALLEYFK; name change
END DESCRIPTION:
DSS File=dss
DSS Export Rating Curves= 0
DSS Export Rating Curve Sorted= 0
DSS Export Volume Flow Curves= 0
DXF OffsetX= 0
DXF OffsetY= 0
DXF ScaleX= 0
DXF ScaleY= 0

--- MUDLKRN.p01 (plan) ---

Plan Title=Floodplain
Program Version=6.20
Short Identifier=Floodplain
Geom File=g01
Flow File=f01
Subcritical Flow
K Sum by GR= 0
Std Step Tol= 0.01
Critical Tol= 0.01
Num of Std Step Trials= 20
Max Error Tol= 0.3
Flow Tol Ratio= 0.001
Split Flow NTrial= 30
Split Flow Tol= 0.02
Split Flow Ratio= 0.02
Log Output Level= 0
Friction Slope Method= 1
Unsteady Friction Slope Method= 2
Unsteady Bridges Friction Slope Method= 1
Parabolic Critical Depth
Global Vel Dist= 0 , 0 , 0
Global Log Level= 0
CheckData=True
Encroach Param=-1 ,0,0, 0
Computation Interval=0.1SEC
Output Interval=1SEC
Instantaneous Interval=Max Profile
Mapping Interval=1HOUR
Computation Time Step Use Courant=        0
Computation Time Step Use Time Series=    0
Computation Time Step Count To Double=0
Computation Time Step Max Doubling=0
Computation Time Step Max Halving=0
Computation Time Step Residence Courant=0
Run HTab= 0
Run UNet= 0
Run Sediment= 0
Run PostProcess= 0
Run WQNet= 0
Run RASMapper=-1
UNET Theta= 0
UNET Theta Warmup= 0
UNET ZTol= 0
UNET ZSATol= 0
UNET MxIter= 0
UNET Max Iter WO Improvement= 0
UNET MaxInSteps= 0
UNET DtIC= 0
UNET DtMin= 0
UNET MaxCRTS= 0
UNET WFStab= 0
UNET SFStab= 0
UNET WFX= 1
UNET SFX= 1
UNET Gravity=32.174
UNET 1D Methodology=Finite Difference
UNET DSS MLevel= 1
UNET Pardiso=0
UNET DZMax Abort= 0
UNET Use Existing IB Tables= 0
UNET Froude Reduction=False
UNET Froude Limit= 0
UNET Froude Power= 0
UNET D1 Cores= 0
UNET WindReference=Eulerian
UNET WindDragFormulation=Hsu (1988)
UNET D2 Coriolis=0
UNET D2 Cores= 0
UNET D2 Theta= 1
UNET D2 Theta Warmup= 1
UNET D2 Z Tol= 0.01
UNET D2 Volume Tol= 0.01
UNET D2 Max Iterations= 20
UNET D2 Equation= 0
UNET D2 RampUpFraction=0.1
UNET D2 TimeSlices= 1
UNET D2 Turbulence Formulation=Non-Conservative (original)
UNET D2 Eddy Viscosity=0.3
UNET D2 Transverse Eddy Viscosity=0.1
UNET D2 Smagorinsky Mixing=0
UNET D2 BCVolumeCheck=0
UNET D2 Cores=0
UNET D2 SolverType=PARDISO (Direct)
UNET D2 Minimum Iterations= 2147483647
UNET D2 Maximum Iterations= 2147483647
UNET D2 Restart Number= 10
UNET D2 Relaxation Coeff=1.3
UNET D2 SOR Precondition Iterations= 10
UNET D2 ILUT Maximum Fill= 8
UNET D2 ILUT Tolerance=1E-08
UNET D1D2 MaxIter= 0
UNET D1D2 ZTol=0.01
UNET D1D2 QTol=0.1
UNET D1D2 MinQTol=1
DSS File=dss
Write IC File= 0
Write IC File at Fixed DateTime=0
Write IC File at Sim End=0
Echo Input=False
Echo Parameters=False
Echo Output=False
Write Detailed= 0
HDF Write Warmup=0
HDF Write Time Slices=0
HDF Flush=0
HDF Compression= 1
HDF Chunk Size= 1
HDF Spatial Parts= 1
HDF Use Max Rows=0
HDF Fixed Rows= 1
Calibration Method= 0
Calibration Iterations= 20
Calibration Max Change=0.05
Calibration Tolerance=0.2
Calibration Maximum=1.5
Calibration Minimum=0.5
Calibration Optimization Method= 1
WQ AD Non Conservative
WQ ULTIMATE=-1
WQ Max Comp Step=1HOUR
WQ Output Interval=15MIN
WQ Output Selected Increments= 0
WQ Output face flow=0
WQ Output face velocity=0
WQ Output face area=0
WQ Output face dispersion=0
WQ Output cell volume=0
WQ Output cell surface area=0
WQ Output cell continuity=0
WQ Output cumulative cell continuity=0
WQ Output face conc=0
WQ Output face dconc_dx=0
WQ Output face courant=0
WQ Output face peclet=0
WQ Output face adv mass=0
WQ Output face disp mass=0
WQ Output cell mass=0
WQ Output cell source sink temp=0
WQ Output nsm pathways=0
WQ Output nsm derived pathways=0
WQ Create Restart=0
WQ Fixed Restart=0
WQ System Summary=0
WQ Write To DSS=0
Sorting and Armoring Iterations= 10
XS Update Threshold= 0.02
Bed Roughness Predictor= 0
Hydraulics Update Threshold= 0.02
Energy Slope Method= 1
Volume Change Method= 1
Sediment Retention Method= 0
Sediment TS Multiplier= 1
Warm Up Method= 0
XS Weighting Method= 0
Number of US Weighted Cross Sections= 1
Number of DS Weighted Cross Sections= 1
Upstream XS Weight=0
Main XS Weight=1
Downstream XS Weight=0
Number of DS XS's Weighted with US Boundary= 1
Upstream Boundary Weight= 1
Weight of XSs Associated with US Boundary= 0
Number of US XS's Weighted with DS Boundary= 1
Downstream Boundary Weight= 0.5
Weight of XSs Associated with DS Boundary= 0.5
Percentile Method= 0
Sediment Output Level= 3
Mass or Volume Output= 0
Output Increment Type= 1
Profile and TS Output Increment= 1
Transport Output Increment 1
XS Output Flag= 0
XS Output Increment= 10
Read HDF5 Sediment Hotstart= 0
Sediment Hotstart Type= 0
Write Gradation File= 0
Read Gradation Hotstart= 0
Write HDF5 File= 1
Write Binary Output= 1
Write DSS Sediment File= 0
DSS Sediment Output Type= 1
SV Curve= 0
Specific Gage Flag= 0
Subcell Erosion Methods= 0
Subcell Deposition Methods= 0
Advection Scheme= 1
Matrix Solver= 0
Implicit Weighting Factor= 1
Maximum Outer Loop Convergence Iterations= 5
Convergence Maximum Absolute= 0.001
Convergence RMSE= 0.0001
Grain Fractions Max Abs Error= 0.001
Max Subgrid Regions= 1
Max Subgrid Length Scale= 3.402823E+38
Initial Layer Thickness= 3.402823E+38
Min Layer Thickness= 3.402823E+38
Max Layer Thickness= 3.402823E+38
Number of Layers= 5

--- MUDLKRN.f01 (steady flow) ---

Flow Title=Flow
Program Version=6.20
Number of Profiles= 1
Profile Names=P100yr
River Rch & RM=MUDLKRN,Main            ,5113
     401
River Rch & RM=MUDLKRN,Main            ,1473
     605
River Rch & RM=MUDLKRN,Main            ,0
     971
Boundary for River Rch & Prof#=MUDLKRN,Main            , 1
Up Type= 0
Dn Type= 1
Dn Known WS=2575.2
DSS Import GetInterval= 0
DSS Import GetPeak= 0
DSS Import FillOption= 0

--- MUDLKRN.g01 (geometry) ---

Geom Title=Geometry
Program Version=6.20

River Reach=MUDLKRN         ,Main
Reach XY= 30
2225830.54023223563340.356162826 2225751.6333499563204.924289852
2225709.63690172563199.7434689042225680.31447545563099.508114752
2225622.99100001 563057.679000022225561.65799998563045.172000006
     2225470.773563082.4979999962225384.34900001563032.151000008
2225224.19300003 563065.571000012225072.71700002563028.678000003
2224978.36700003562769.2020000072224857.53400001562702.014000013
2224649.72100003562686.3890000132224536.70000003562494.202000022
2224321.07600005562292.1190000032224162.54382471562015.602485538
     2224007.013561907.744000003     2223809.617561867.119000018
2223724.72100002561782.7440000182223628.88799998561806.702000022
2223491.38800003561771.8059999942223379.37700002561788.228000015
2223141.77646686561630.2057077552223075.31200002561502.694999993
2223060.69569258561382.3742909432222828.99500003561096.842000008
2222586.49759866560972.8300762032222328.99200003560889.268000022
2222191.35509333560958.9532770962222073.49802933560942.424915059

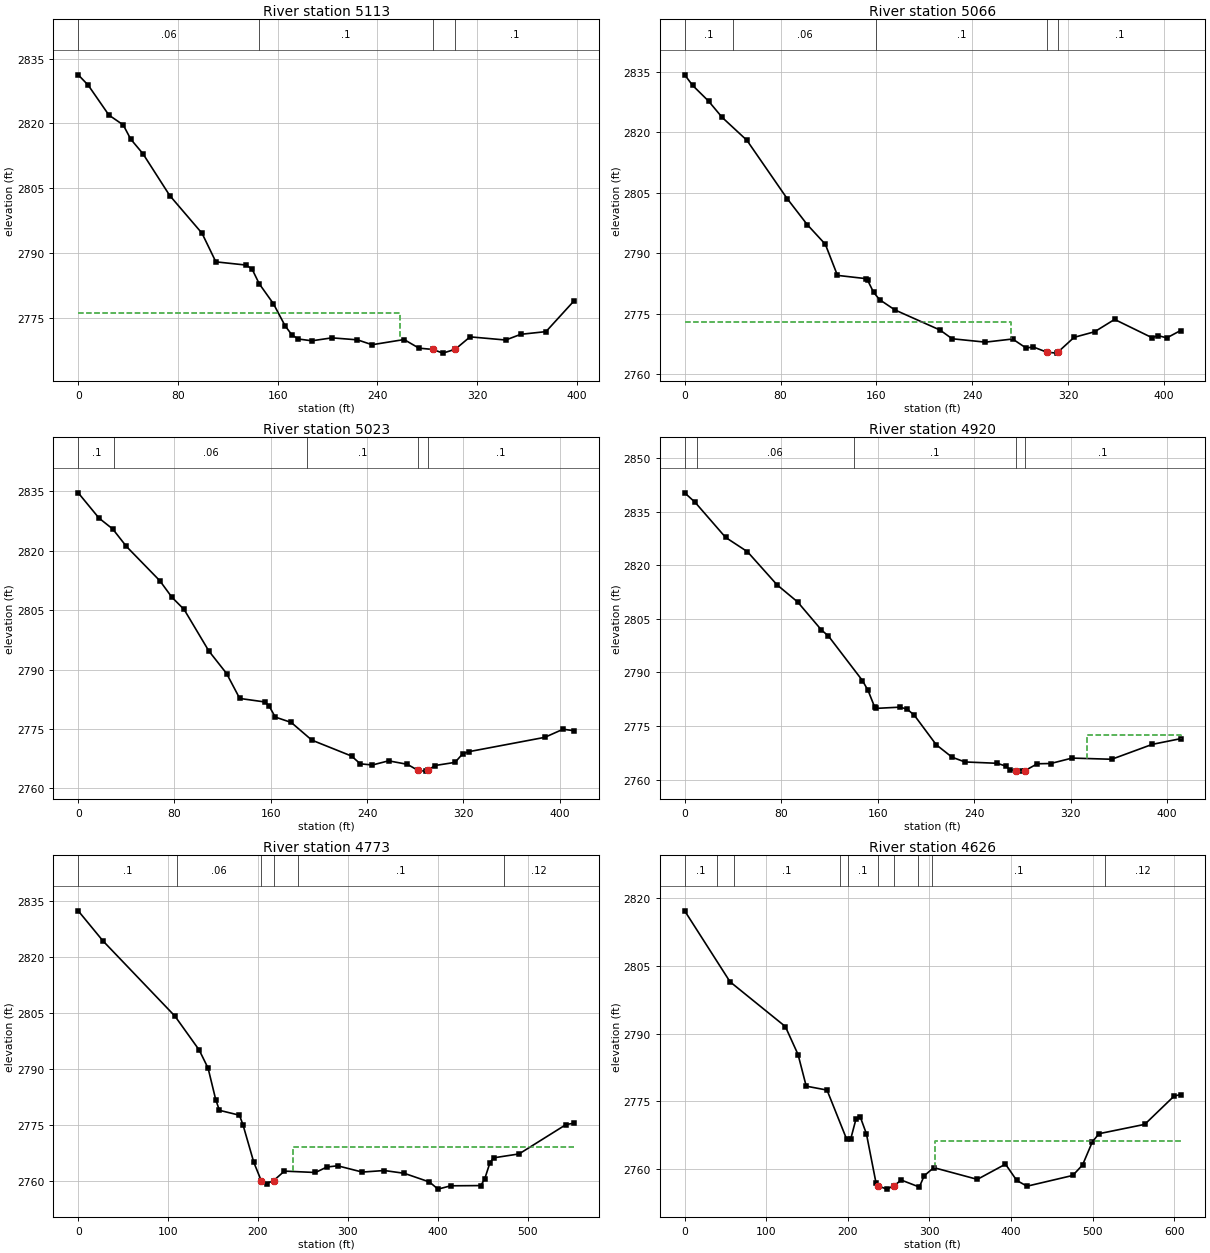
Type RM Length L Ch R = 1 ,5113    ,49.9,46.5,47.9
XS GIS Cut Line= 5
2226015.84126234563106.6489468882225932.74452292563225.767670028
2225843.01247353563325.9698561182225816.58570638563349.983745514
2225827.26641105563431.635736771
#Sta/Elev= 30
       0 2831.24       8 2828.85    24.6 2821.94    36.1 2819.66    42.1 2816.38
    51.9 2813.01    73.4 2803.34    99.3 2794.62   110.4 2788.01   134.8 2787.26
   139.5 2786.31   145.2 2782.94   156.6 2778.32   165.9 2773.25   171.3 2771.15
   176.4 2770.18   187.4 2769.76   203.5 2770.44     224 2769.98   235.7 2768.85
   261.4 2770.05   273.3 2768.06   284.5 2767.76   292.5 2766.91   302.4  2767.8
   314.3 2770.67   342.9 2769.94     355 2771.26   375.2 2771.88   397.8 2779.02
#Mann= 4 ,-1,0
       0     .06       0  145.24      .1       0   284.5    .045       0
   302.4      .1       0
#XS Ineff= 2 , 0
          257.74 2776.26
Permanent Ineff=
       F       F
Bank Sta=284.5,302.4
XS Rating Curve= 0 ,0
Exp/Cntr=0.3,0.1

Type RM Length L Ch R = 1 ,5066    ,43.4,43.1,43.4
XS GIS Cut Line= 6
2225986.76866488563075.9316036712225833.43499842563276.134345443
2225811.89794525563294.2450492492225772.25018827563325.082193567
2225749.73417813563342.2139404112225758.54479079563396.546051829
#Sta/Elev= 30
       0 2834.23     6.6 2831.62    19.9 2827.73    31.3 2823.68    51.9 2818.02
    85.5 2803.58   102.3 2797.12   117.4 2792.25   127.5 2784.55   151.1 2783.75
   152.7 2783.32   157.7 2780.34   162.7 2778.53   175.4    2776   213.1 2771.01
   223.2 2768.85     251 2768.01   273.7 2768.79     285 2766.54   290.8 2766.83
   302.2 2765.53   310.4 2765.29  311.492765.535     325  2769.2   342.1 2770.58
   358.8 2773.64   390.2 2769.09   394.9 2769.64   402.4 2769.07   413.9 2770.89
#Mann= 5 ,-1,0
       0      .1       0      40     .06       0     160      .1       0
   302.2    .045       0  311.49      .1       0
#XS Ineff= 2 , 0
          272.59 2772.99
Permanent Ineff=
       F       F
Bank Sta=302.2,311.49
XS Rating Curve= 0 ,0
Exp/Cntr(USF)=0,0
Exp/Cntr=0.3,0.1

Type RM Length L Ch R = 1 ,5023    ,103.2,103.8,102
XS GIS Cut Line= 6
2225950.63535463563051.447568796 2225797.9059826563249.837427304
2225776.36892942 563267.948131112225736.72117244563298.785275429
 2225714.2051623563315.9170222722225723.01577497 563370.24913369
#Sta/Elev= 30
       0 2834.63    17.3 2828.24    28.7 2825.49    40.1 2821.08    67.8 2812.44
    77.9 2808.25      88 2805.18   108.5 2794.72   123.3 2789.01   134.2 2782.72
   154.9 2781.84   158.6 2780.83   163.7 2778.02     177 2776.66   194.1  2772.2
   227.1 2768.18   234.4 2766.21   244.5 2765.92   257.9 2766.97   273.5 2766.09
   282.4 2764.55   288.9 2764.37  290.352764.558   296.6 2765.79   313.1 2766.58
   319.4 2768.71   324.4 2769.27   387.7  2772.9   402.9 2774.95   412.1 2774.56
#Mann= 5 ,-1,0
       0      .1       0      30     .06       0     190      .1       0
   282.4    .045       0  290.35      .1       0
Bank Sta=282.4,290.35
XS Rating Curve= 0 ,0
Exp/Cntr(USF)=0,0
Exp/Cntr=0.3,0.1

Type RM Length L Ch R = 1 ,4920    ,147,146.9,144.5
XS GIS Cut Line= 4
 2225906.7071578562999.6013988252225728.37257537 563200.12203717
2225687.19097437563261.4223548462225680.39747709563329.959694674
#Sta/Elev= 30
       0 2840.23     8.6 2837.59    33.9 2827.76      52 2823.76    76.6 2814.47
    93.6  2809.7   113.4 2801.83   119.1 2800.18   147.4 2787.67     152 2784.93
   157.4 2780.35   158.7 2779.91   178.4 2780.25   184.4  2779.7   190.4 2777.97
   208.5 2769.74   221.6 2766.25   232.3 2764.92   259.1 2764.54   266.4 2763.73
   269.6  2762.7     275 2762.49   279.3 2762.35  282.092762.491   292.3 2764.41
   303.4 2764.48   321.1    2766     354 2765.67   387.6 2769.84   411.1 2771.43
#Mann= 5 ,-1,0
       0      .1       0      10     .06       0     140      .1       0
     275    .045       0  282.09      .1       0
#XS Ineff= 2 , 0
                          333.48         2772.57
Permanent Ineff=
       F       F
Bank Sta=275,282.09
XS Rating Curve= 0 ,0
Exp/Cntr=0.3,0.1

Type RM Length L Ch R = 1 ,4773    ,156.8,146.5,136.3
XS GIS Cut Line= 5
2225809.14662616   562933.7752042225687.91319461563055.643385683
2225645.19904122563102.0252644622225521.80597949563294.209787068
2225511.66126996563382.114415089
#Sta/Elev= 30
       0 2832.33    27.4 2824.32   107.7 2804.13   134.6 2795.08   144.5 2790.23
     153 2781.81   157.1 2778.95   179.4 2777.64   183.3  2775.1   195.4    2765
  203.63 2760.13   209.6 2759.36   217.5 2760.15   229.4 2762.68     264 2762.31
   276.7 2763.78   288.7  2764.1   316.1 2762.42   340.5 2762.84   362.7  2762.1
   390.8 2759.77   400.3 2757.86   414.5 2758.75   447.9 2758.81   452.2 2760.53
     458 2764.85   462.1 2766.23   490.5 2767.28   542.8 2775.14   551.8 2775.51
#Mann= 6 ,-1,0
       0      .1       0     110     .06       0  203.63    .045       0
   217.5     .06       0  244.95      .1       0  473.34     .12       0
#XS Ineff= 2 , 0
                          239.01         2769.25
Permanent Ineff=
       F       F
Bank Sta=203.63,217.5
XS Rating Curve= 0 ,0
Exp/Cntr=0.3,0.1

Type RM Length L Ch R = 1 ,4626    ,185.7,193.9,197.5
XS GIS Cut Line= 5
2225658.76166224562860.5281414732225518.40169109563037.220511319
2225547.81600214563098.4650376332225476.72469884563254.175912603
2225468.08842459563397.127827805
#Sta/Elev= 30
       0 2817.18    55.6 2801.47   123.4 2791.56     139 2785.36     149 2778.36
   174.5 2777.49   198.7 2766.56   203.5 2766.62   210.1 2771.14   215.4 2771.48
   222.8 2767.81   234.5    2757  236.782756.293   247.8 2755.56   256.7 2756.31
   265.5 2757.57   287.7 2756.02   293.6 2758.51   305.4 2760.32   358.8 2757.72
   393.3 2761.09   407.1 2757.48   419.7 2756.21   475.8 2758.59   487.8 2760.92
   499.8 2766.03   507.9 2767.83     564  2769.9     600 2776.16     608  2776.5
#Mann= 10 ,-1,0
       0      .1       0      40     .06       0      60      .1       0
     190     .06       0     200      .1       0  236.78    .045       0
   256.7      .1       0  285.66     .06       0   303.6      .1       0
  514.77     .12       0
#XS Ineff= 2 , 0
                          306.28         2766.29
Permanent Ineff=
       F       F
Bank Sta=236.78,256.7
XS Rating Curve= 0 ,0
Exp/Cntr=0.3,0.1

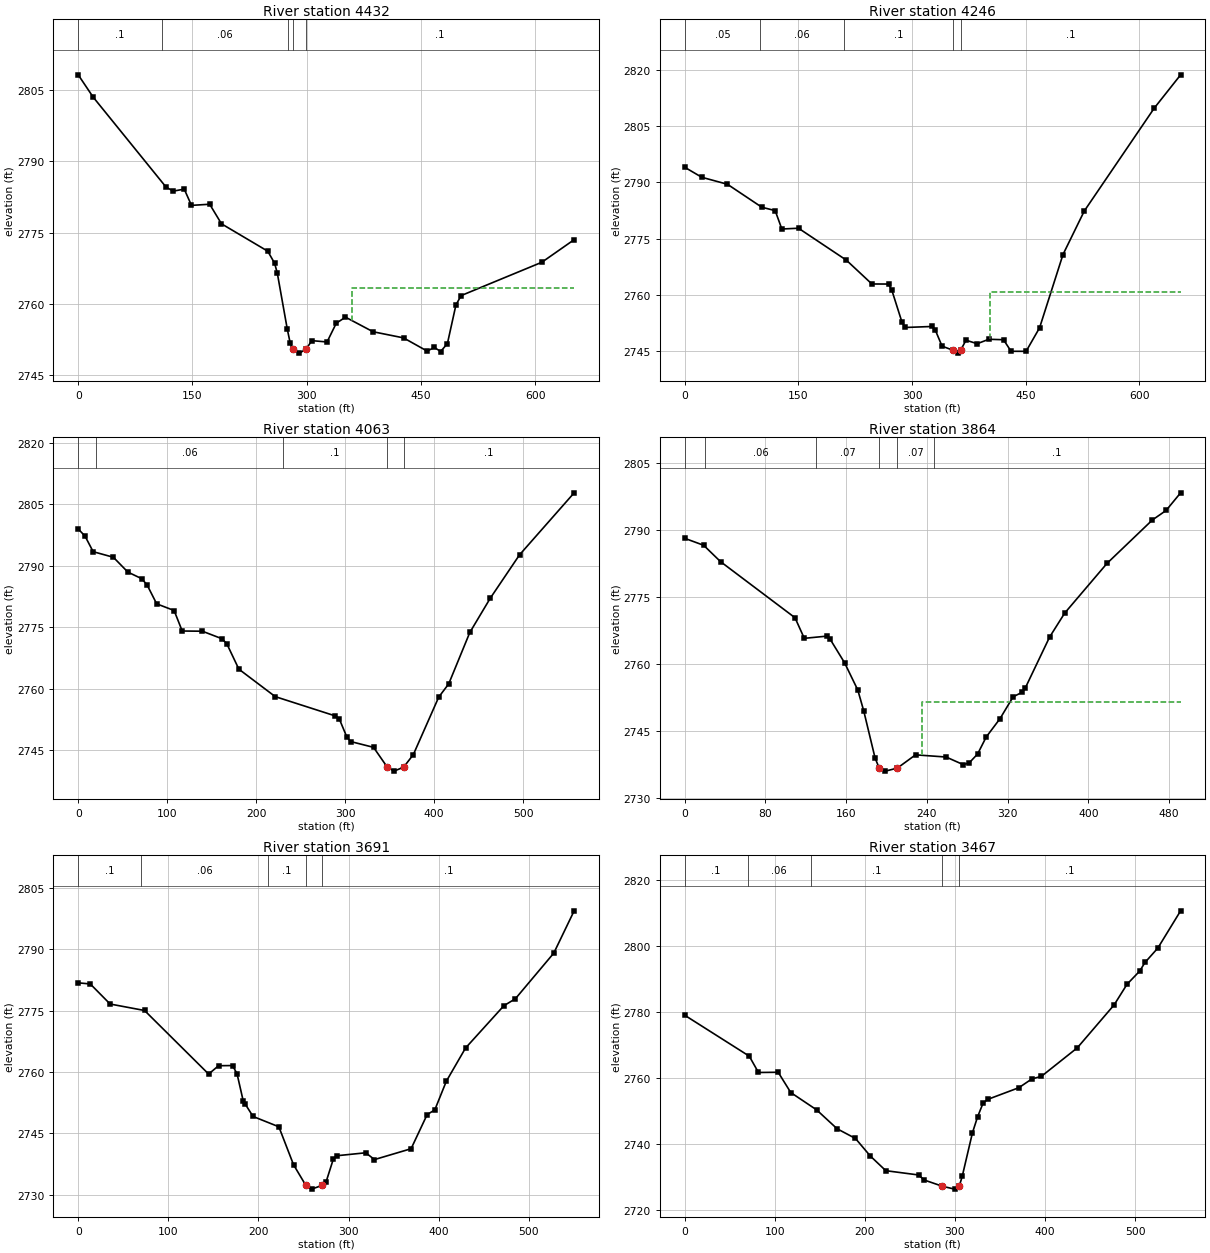
Type RM Length L Ch R = 1 ,4432    ,185,186.6,185.6
XS GIS Cut Line= 4
2225500.06805582562780.7194540932225359.90330042562994.977745541
2225334.20302083563212.2430084032225313.61492979563387.330258961
#Sta/Elev= 30
       0 2808.22    19.7 2803.51   115.3 2784.59   124.8 2783.74   139.2 2784.16
   148.7 2780.74   172.6 2780.98   188.1 2776.86   248.8  2771.1   257.8 2768.58
   261.4 2766.46   274.4 2754.76   278.4 2751.68   281.62750.564   290.5 2749.64
   299.52750.527   306.6 2752.27   326.7 2751.99   338.8 2755.94   350.9 2757.21
   387.1 2754.14   427.1 2752.85     458 2750.08   467.7 2750.83   475.8 2749.98
   484.7 2751.65   495.9 2759.78   502.7 2761.75   608.7 2768.77   651.1 2773.52
#Mann= 5 ,-1,0
       0      .1       0     110     .06       0  276.03      .1       0
   281.6    .045       0   299.5      .1       0
#XS Ineff= 2 , 0
                          359.86          2763.4
Permanent Ineff=
       F       F
Bank Sta=281.6,299.5
XS Rating Curve= 0 ,0
Exp/Cntr=0.3,0.1

Type RM Length L Ch R = 1 ,4246    ,175.9,182.6,189.2
XS GIS Cut Line= 5
2225330.31841535562724.5953270532225191.92366246563026.719741346
2225173.56560743563061.8667973792225118.34542198563137.061307636
2224985.30952444563271.440199981
#Sta/Elev= 30
       0 2794.06    22.6 2791.39    56.4 2789.53   101.8 2783.41   119.4 2782.51
   128.2 2777.61   150.2 2777.82   213.3 2769.32     247 2762.97     269 2762.95
   273.4 2761.27   286.6 2752.88     291 2751.38   326.2 2751.65   330.6 2750.74
   339.6 2746.41   354.7 2745.27   360.6 2744.55  363.99 2745.27   371.2 2747.99
     386 2747.06   401.3 2748.24   420.7 2748.12   430.7 2745.04   450.5 2745.03
   468.3  2751.3   499.2 2770.82   527.3 2782.41   619.6 2809.81   654.4 2818.68
#Mann= 5 ,-1,0
       0     .05       0     100     .06       0     210      .1       0
   354.7    .045       0  363.99      .1       0
#XS Ineff= 2 , 0
                          403.18         2760.94
Permanent Ineff=
       F       F
Bank Sta=354.7,363.99
XS Rating Curve= 0 ,0
Exp/Cntr=0.3,0.1

Type RM Length L Ch R = 1 ,4063    ,203.2,198.8,193.6
XS GIS Cut Line= 4
2225253.02911112562698.4147988172225127.01004856562931.076252889
2225015.17335684562974.304547983 2224894.1410585563097.921832616
#Sta/Elev= 30
       0    2799     7.7 2797.23    16.8 2793.44    39.5 2792.08    55.8 2788.46
    71.4 2786.84    77.4 2785.33    88.2  2780.7   107.8 2779.07   116.9 2774.06
   139.6 2774.01   161.4 2772.19   166.9 2771.01   180.6 2764.74   221.5 2758.03
   289.1 2753.31   293.4 2752.63   301.9  2748.2   306.2 2747.06     332 2745.64
  347.45 2740.79     355 2739.83  365.772740.791   376.7 2743.86   405.3 2757.93
   416.5 2761.15   440.2  2773.7   463.1 2782.04   496.1 2792.67   557.5 2807.82
#Mann= 5 ,-1,0
       0     .05       0      20     .06       0     230      .1       0
  347.45    .045       0  365.77      .1       0
Bank Sta=347.45,365.77
XS Rating Curve= 0 ,0
Exp/Cntr=0.3,0.1

Type RM Length L Ch R = 1 ,3864    ,179.6,173.8,167.3
XS GIS Cut Line= 4
2225085.55369746562602.3892912452224997.64761084562755.556409225
2224922.54198482562855.5568318412224839.76835461563026.149234344
#Sta/Elev= 30
       0 2788.09    18.8 2786.53    35.5 2782.88   109.3 2770.34   118.5 2765.74
   140.8 2766.23   143.7 2765.69   158.4 2760.28   171.5 2754.19   177.4 2749.51
   188.6 2739.01  192.712736.747   198.8 2736.07  210.662736.745   228.7 2739.71
     259 2739.22   275.9 2737.53   281.7 2737.88   290.2  2739.9   298.7 2743.69
   312.4  2747.8   325.4 2752.68   334.6 2753.72   337.6 2754.73   361.5 2766.02
   376.5 2771.39   418.4 2782.49   463.3 2792.18   476.9 2794.31   491.3 2798.25
#Mann= 6 ,-1,0
       0      .1       0      20     .06       0     130     .07       0
  192.71    .045       0  210.66     .07       0   246.6      .1       0
#XS Ineff= 2 , 0
                          234.66         2751.48
Permanent Ineff=
       F       F
Bank Sta=192.71,210.66
XS Rating Curve= 0 ,0
Exp/Cntr=0.3,0.1

Type RM Length L Ch R = 1 ,3691    ,215.5,223.3,231.1
XS GIS Cut Line= 4
2224997.96684742   562508.9676162224835.24308158562660.887973124
 2224840.2969841 562758.067092232224761.43693419562974.390572967
#Sta/Elev= 30
       0 2781.78    13.4  2781.5    35.4  2776.6    73.6 2775.02   144.7 2759.49
   155.7 2761.53   171.2 2761.57   176.2 2759.57     183 2752.98   185.4 2752.11
     194 2749.13   222.6 2746.61   238.9 2737.33   252.42732.342     259 2731.38
  270.92 2732.33     275 2733.15     283 2738.71     287 2739.54     319 2740.26
   328.7  2738.6   369.3 2741.25   387.1 2749.59   395.6 2750.74   408.4 2757.74
   429.7 2765.85   472.2 2776.18     485 2777.89   527.6 2789.04   550.2 2799.37
#Mann= 5 ,-1,0
       0      .1       0      70     .06       0     210      .1       0
   252.4    .045       0  270.92      .1       0
Bank Sta=252.4,270.92
XS Rating Curve= 0 ,0
Exp/Cntr=0.3,0.1

Type RM Length L Ch R = 1 ,3467    ,197.7,197.9,198.2
XS GIS Cut Line= 4
2224856.09902166562475.1879225122224683.29879476562613.770291776
2224617.93312633562679.2833042282224477.10886426562869.293181039
#Sta/Elev= 30
       0 2779.05    71.7 2766.62    81.9 2761.66   103.8 2761.73   117.8 2755.57
   146.5 2750.31   169.2 2744.58   189.6 2741.63   206.2 2736.27   223.3 2731.85
   259.9 2730.54   265.7 2729.04  286.06 2727.13   299.6 2726.25  304.832727.128
   308.1 2730.09   319.5 2743.38   325.2 2748.21   331.3 2752.37   336.3 2753.48
     371 2757.04   385.3 2759.68   396.1  2760.5   435.9 2769.15   476.8 2782.19
   491.1 2788.44   505.1 2792.43   511.1 2795.08   525.3 2799.43   550.6 2810.74
#Mann= 5 ,-1,0
       0      .1       0      70     .06       0     140      .1       0
  286.06    .045       0  304.83      .1       0
Bank Sta=286.06,304.83
XS Rating Curve= 0 ,0
Exp/Cntr=0.3,0.1

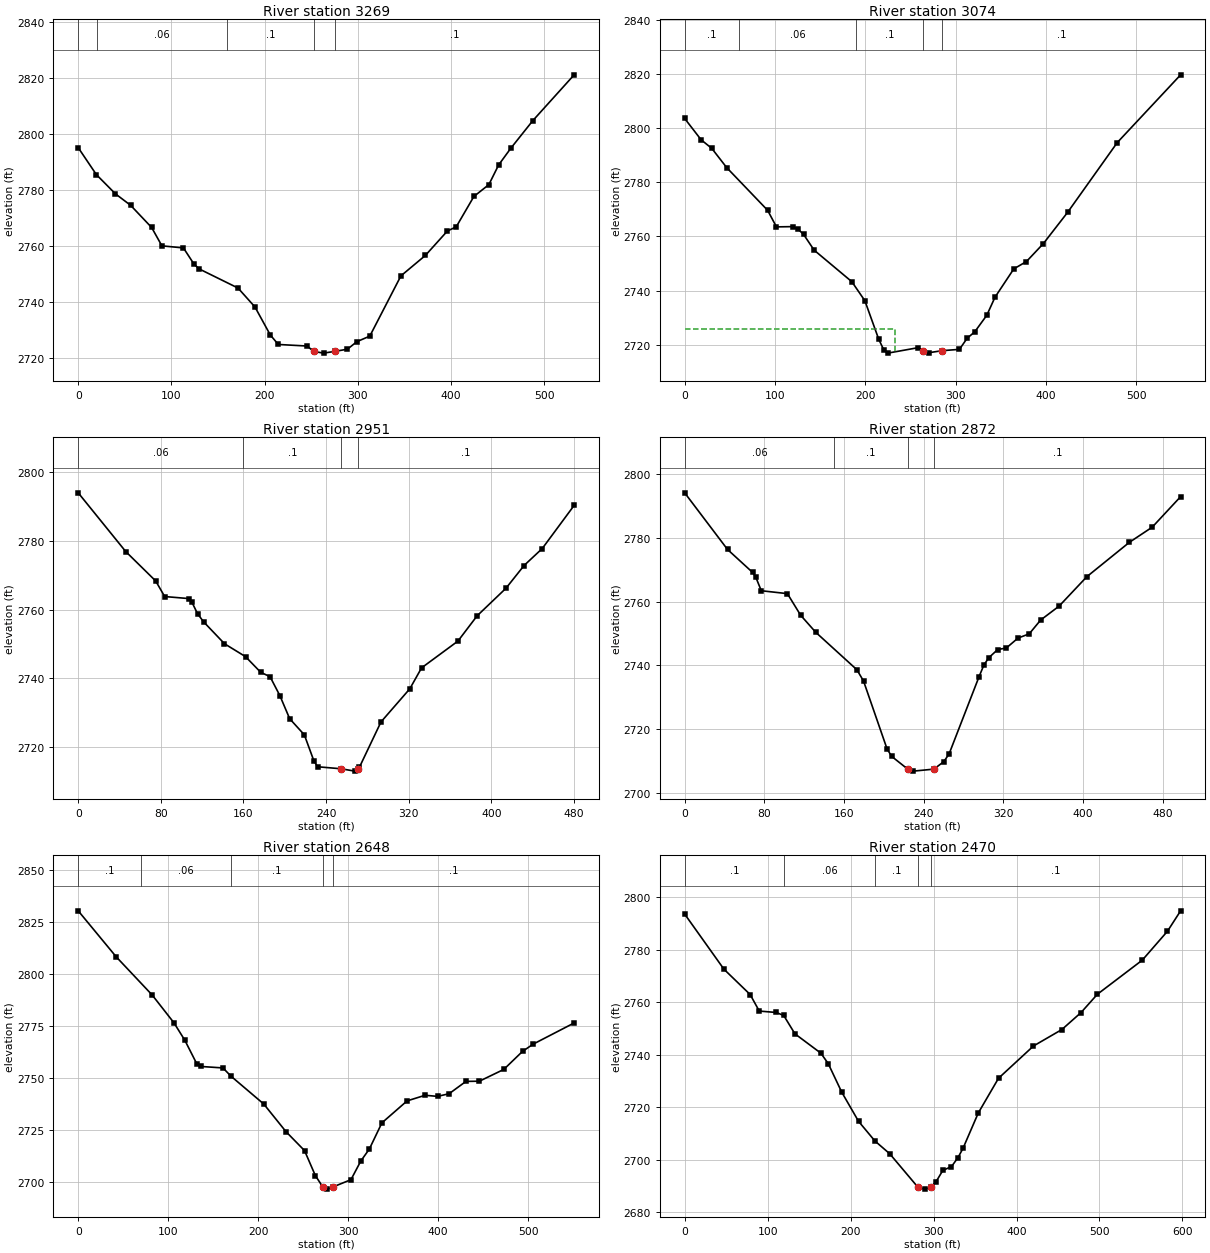
Type RM Length L Ch R = 1 ,3269    ,196.7,195.9,194.5
XS GIS Cut Line= 4
2224718.97437341562304.3808938022224547.62996236562482.763541902
2224513.01661215562512.6259864842224358.25770123562694.942025043
#Sta/Elev= 30
       0 2795.19    19.5 2785.56    39.9 2778.72    56.3 2774.59    78.8 2766.69
    89.8 2760.14   112.9  2759.4   124.2 2753.64   129.8  2751.9   171.5 2745.07
   189.7  2738.3   206.1 2728.34   214.7 2724.93   245.8 2724.37  252.55 2722.46
   263.3 2721.84  275.262722.459   288.9 2723.24     299 2725.93   312.9 2727.91
   346.3 2749.42   372.5  2756.7   396.2 2765.45   405.6  2766.9   424.6 2777.76
   440.7 2782.01   451.2 2789.04   464.3 2795.01   487.9 2804.86   532.2 2821.19
#Mann= 5 ,-1,0
       0      .1       0      20     .06       0     160      .1       0
  252.55    .045       0  275.26      .1       0
Bank Sta=252.55,275.26
XS Rating Curve= 0 ,0
Exp/Cntr=0.3,0.1

Type RM Length L Ch R = 1 ,3074    ,118.3,122.4,124.5
XS GIS Cut Line= 4
2224597.77645541562169.049986769 2224436.4885858562314.884770975
2224367.83715701562387.4202866522224229.48540139562573.371667523
#Sta/Elev= 30
       0  2803.5    18.2 2795.64      30 2792.47    46.5 2785.38    91.8 2769.63
   101.6  2763.5   119.5 2763.59   125.4 2762.67   131.6 2760.75   143.3 2754.92
   185.1 2743.26   199.5 2736.25   214.9 2721.98   220.6 2718.02   224.9 2716.91
   258.6 2718.93  263.572717.853   270.3 2717.06285.20362717.822   304.2  2718.3
   312.7 2722.37   321.2 2724.79   334.5 2730.88   343.6 2737.55   364.4    2748
   378.4 2750.71   397.2 2757.36     424 2768.87     479 2794.63   549.1 2819.61
#Mann= 5 ,-1,0
       0      .1       0      60     .06       0     190      .1       0
  263.57    .045       0285.2036      .1       0
#XS Ineff= 2 , 0
          233.08 2725.73
Permanent Ineff=
       F       F
Bank Sta=263.57,285.2036
XS Rating Curve= 0 ,0
Exp/Cntr=0.3,0.1

Type RM Length L Ch R = 1 ,2951    ,78.6,78.9,79.6
XS GIS Cut Line= 4
 2224536.8348399562134.3225223712224346.77133046562255.272028374
2224296.25121136 562278.784369292224194.49546584562449.919032223
#Sta/Elev= 30
       0 2793.99      46 2776.91      75 2768.35    83.7 2763.82   106.9 2763.23
   109.8 2762.34   115.5 2758.84   121.3 2756.49   141.6 2750.09     162 2746.33
   176.7 2741.77   185.7 2740.51   195.2 2735.01   204.7 2728.28   218.9 2723.59
   228.1 2716.05   231.7  2714.3   254.6 2713.71   267.7 2713.03   270.8 2713.73
   272.3 2714.21   293.1 2727.34     321 2736.98   332.4 2743.07   367.6 2750.86
   386.2 2758.22   414.1 2766.23   431.6 2772.84   449.2 2777.78   480.1 2790.34
#Mann= 4 ,-1,0
       0     .06       0     160      .1       0   254.6    .045       0
   270.8      .1       0
Bank Sta=254.6,270.8
XS Rating Curve= 0 ,0
Exp/Cntr(USF)=0,0
Exp/Cntr=0.3,0.1

Type RM Length L Ch R = 1 ,2872    ,226,224.6,220
XS GIS Cut Line= 4
2224480.71491215562079.7588700332224305.65053936562188.451228983
2224251.77810263562212.0551831022224118.19180542562402.902535543
#Sta/Elev= 30
       0 2794.18      43 2776.38    68.2 2769.16    71.1 2767.88    76.9 2763.41
   103.1  2762.5   116.4 2755.71   131.6 2750.34   172.8  2738.6   179.5 2735.06
   203.1 2713.73   207.7 2711.37  223.87 2707.35   229.5 2706.72  250.14 2707.35
   260.1  2709.7   265.4 2712.12   295.5 2736.42   300.4 2740.11   305.3 2742.37
   314.2 2744.94   322.8  2745.4   334.6 2748.54   345.8 2749.85   357.3  2754.2
   375.8 2758.57   403.7 2767.83   446.3 2778.61   469.3 2783.39   497.8 2792.98
#Mann= 4 ,-1,0
       0     .06       0     150      .1       0  223.87    .045       0
  250.14      .1       0
Bank Sta=223.87,250.14
XS Rating Curve= 0 ,0
Exp/Cntr=0.3,0.1

Type RM Length L Ch R = 1 ,2648    ,179.7,177.8,176
XS GIS Cut Line= 4
2224410.76617005561894.996701416 2224178.6441979561999.543444835
2224146.84229742562025.0127108232224014.52874972562244.130343211
#Sta/Elev= 30
       0 2830.47    42.3 2808.32    82.3 2789.96   106.4 2776.64   118.5 2768.26
   131.9 2756.83   136.7 2755.63   160.9 2754.93     170  2750.9   206.3 2737.56
     231 2724.28   251.6 2715.17   263.6 2703.18  271.94 2697.68   276.4 2696.66
   282.8 2697.64   303.2 2701.21   314.2 2710.22   323.6 2715.91   337.6 2728.53
   365.6 2739.09   385.6 2741.78   399.4 2741.26   412.3 2742.53     431 2748.45
     446 2748.56   473.1 2754.22   493.9 2762.88   505.8 2766.39   551.3 2776.56
#Mann= 5 ,-1,0
       0      .1       0      70     .06       0     170      .1       0
  271.94    .045       0   282.8      .1       0
Bank Sta=271.94,282.8
XS Rating Curve= 0 ,0
Exp/Cntr=0.3,0.1

Type RM Length L Ch R = 1 ,2470    ,199.7,197.3,194.5
XS GIS Cut Line= 4
2224262.15589807561769.947222408 2224028.7263223561891.160625147
2224002.04506088561932.5431966652223891.51430102562195.836372678
#Sta/Elev= 30
       0 2793.63    47.3 2772.65    78.9    2763    89.9  2756.7   110.4 2756.16
   119.4 2755.01   132.9 2748.03   164.1 2740.68     173 2736.71   189.3 2725.82
   209.6  2714.7   229.3 2707.23   247.1 2702.38  280.842689.739   289.2 2688.89
  296.61 2689.74   302.5 2691.45   311.2 2696.03   321.6 2697.47   329.5 2700.92
   335.6  2704.5   353.9 2717.89   378.3 2731.11   420.4 2743.39   454.7 2749.67
   477.8 2756.14   497.5 2763.11   551.6 2776.09   581.9 2787.08   597.8 2794.87
#Mann= 5 ,-1,0
       0      .1       0     120     .06       0     230      .1       0
  280.84    .045       0  296.61      .1       0
Bank Sta=280.84,296.61
XS Rating Curve= 0 ,0
Exp/Cntr=0.3,0.1

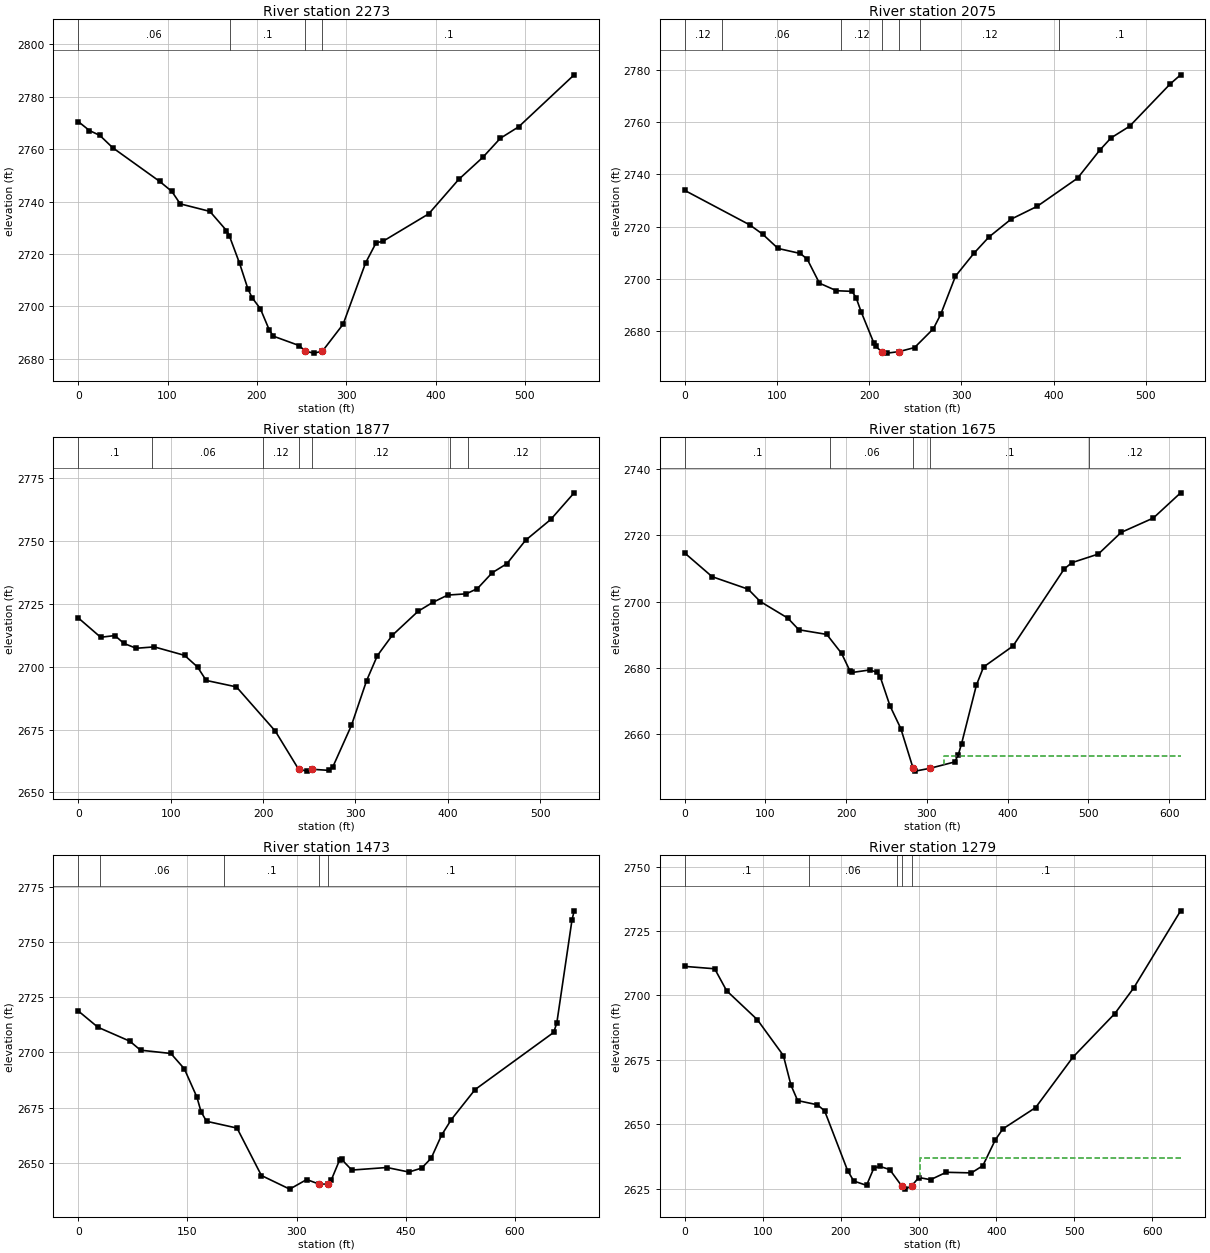
Type RM Length L Ch R = 1 ,2273    ,197.7,197.2,187.2
XS GIS Cut Line= 4
2223953.04659726561640.7028384282223835.51744595561826.072796959
2223820.62887421561889.4067855352223763.23672079562153.918572873
#Sta/Elev= 30
       0 2770.53    12.6 2767.09    24.2 2765.24    38.5 2760.56    91.3 2747.65
   104.8 2743.86   114.2 2739.11   147.4 2736.23     166 2728.92   169.1 2726.98
   180.7 2716.36     190 2706.63   194.7 2703.27   203.9 2699.09   213.7 2691.13
   218.4 2688.61   247.3 2685.02  254.36 2682.85   263.8 2682.13  273.31 2682.85
   296.6 2693.18   321.7 2716.57   333.4 2724.19   341.6 2724.91   392.4  2735.3
     426 2748.45   452.9 2756.85   472.6 2764.15   493.1 2768.52   555.2 2788.36
#Mann= 4 ,-1,0
       0     .06       0     170      .1       0  254.36    .045       0
  273.31      .1       0
Bank Sta=254.36,273.31
XS Rating Curve= 0 ,0
Exp/Cntr=0.3,0.1

Type RM Length L Ch R = 1 ,2075    ,197.2,198.1,202.9
XS GIS Cut Line= 4
2223737.64477064561596.3948182772223659.81745014 561765.71252375
2223682.16023187561831.1407241142223659.36535141 562112.39288389
#Sta/Elev= 30
       0  2733.9    70.6 2720.69    84.5 2717.16   101.2 2711.69   125.4 2709.76
   132.9 2707.57   146.1 2698.41   164.6 2695.52   181.4 2695.28   185.8 2692.93
   191.3 2687.49   205.1 2675.53   206.9 2674.26  213.762672.227   219.6 2671.66
   232.3 2672.23   249.2 2673.78   269.6 2680.97   277.6 2686.49   293.6 2701.08
   313.7 2709.88   329.8 2716.04   353.8 2722.86   382.2  2727.8   425.9 2738.54
   450.2 2749.34   462.2 2753.95   482.3 2758.39   526.4 2774.59   537.7 2778.08
#Mann= 7 ,-1,0
       0     .12       0      40     .06       0     170     .12       0
  213.76    .045       0   232.3     .06       0  255.49     .12       0
  405.49      .1       0
Bank Sta=213.76,232.3
XS Rating Curve= 0 ,0
Exp/Cntr=0.3,0.1

Type RM Length L Ch R = 1 ,1877    ,196.8,202.6,205.7
XS GIS Cut Line= 4
2223596.78431325561558.8562852552223478.41759129561753.661484419
2223482.59791521561807.4565786312223465.80780835562061.748629238
#Sta/Elev= 30
       0 2719.48    24.3 2711.75    39.7 2712.43    49.5 2709.29    62.8 2707.37
    82.3 2707.92   115.1 2704.55   129.1 2699.92   138.5 2694.57   171.2    2692
   213.3 2674.39  238.472659.237   247.3 2658.47  253.362659.204   271.6 2658.76
   275.6 2660.21   295.7 2676.69   312.1  2694.5   323.7 2704.41   339.8 2712.49
   367.8 2722.09   383.8 2725.66   399.9 2728.54   419.9 2729.04     432 2731.12
     448 2737.43     464 2741.06   484.1 2750.34   511.4 2758.65   536.7 2769.24
#Mann= 7 ,-1,0
       0      .1       0      80     .06       0     200     .12       0
  238.47    .045       0  253.36     .12       0   401.9      .1       0
   421.9     .12       0
Bank Sta=238.47,253.36
XS Rating Curve= 0 ,0
Exp/Cntr=0.3,0.1

Type RM Length L Ch R = 1 ,1675    ,199.2,201.3,203.5
XS GIS Cut Line= 4
2223486.21505519561491.4093060962223332.94560019561676.935367802
2223275.22645663 561794.205013032223310.26142821562034.594125271
#Sta/Elev= 30
       0 2714.65      34 2707.51    78.6 2703.75    93.6 2700.03   127.7 2695.04
   141.4 2691.52     176 2690.12   194.3 2684.42   204.6 2679.19   207.3 2678.65
   229.3 2679.42   238.5 2678.68   242.4 2677.21   254.3 2668.61   267.7 2661.77
  282.942649.792   285.5 2648.94   303.92649.792   334.5 2651.71     339 2653.94
     343 2657.23   361.3 2674.81   370.2 2680.31   406.6  2686.6   470.1 2709.83
   479.5 2711.72   512.4 2714.33   540.6 2720.84   580.5 2725.18   614.3 2732.77
#Mann= 5 ,-1,0
       0      .1       0     180     .06       0  282.94    .045       0
   303.9      .1       0  501.35     .12       0
#XS Ineff= 2 , 0
                          321.34         2653.54
Permanent Ineff=
       F       F
Bank Sta=282.94,303.9
XS Rating Curve= 0 ,0
Exp/Cntr=0.3,0.1

Type RM Length L Ch R = 1 ,1473    ,190.4,194.1,198.5
XS GIS Cut Line= 4
2223398.33856128561416.3244896622223216.05178984561543.504383754
 2223044.5326834561718.4155244772222846.15635585561799.006160956
#Sta/Elev= 30
       0 2718.75      27 2711.38    70.9 2705.06    85.6 2700.99   127.3  2699.5
   145.8 2692.57   163.1 2679.74   168.8 2673.12   176.3 2668.83   218.2 2665.76
   251.7 2644.31   290.6 2638.15   313.9 2642.48  331.192640.405  342.752640.415
   347.9 2642.44   359.1  2651.3     362 2651.58   375.9 2646.77   424.2 2647.93
   454.3 2645.88   471.9 2647.66     485 2652.15   499.2 2662.53   512.6  2669.6
   545.3 2683.18   653.3 2709.03   657.6 2713.37   678.4 2759.79   681.4 2764.01
#Mann= 5 ,-1,0
       0     .12       0      30     .06       0     200      .1       0
  331.19    .045       0  342.75      .1       0
Bank Sta=331.19,342.75
XS Rating Curve= 0 ,0
Exp/Cntr=0.3,0.1

Type RM Length L Ch R = 1 ,1279    ,200.2,197.8,193.5
XS GIS Cut Line= 4
2223304.57908541561308.0726773912223105.10639359561444.866495216
2222975.89060718561460.9344990262222779.58856101561637.673078202
#Sta/Elev= 30
       0 2711.27    38.5 2710.34    53.8 2701.83    93.2 2690.59   126.6 2676.69
   136.3 2665.25   144.9 2659.21   170.2 2657.58   179.5 2655.23     209 2632.06
   216.9    2628   233.3 2626.33   242.8 2633.11   250.9 2633.64     263 2632.45
  278.342626.136   283.1 2624.86  291.322626.138   300.3 2629.37   315.4 2628.52
   335.5 2631.39   367.8 2631.16   382.5 2633.96   398.6 2644.03   408.3 2648.26
   450.2  2656.5     498 2676.03   551.8 2692.96     576 2702.89   636.2 2732.82
#Mann= 5 ,-1,0
       0      .1       0     160     .06       0  271.87      .1       0
  278.34    .045       0  291.32      .1       0
#XS Ineff= 2 , 0
                          302.36         2637.11
Permanent Ineff=
       F       F
Bank Sta=278.34,291.32
XS Rating Curve= 0 ,0
Exp/Cntr=0.3,0.1

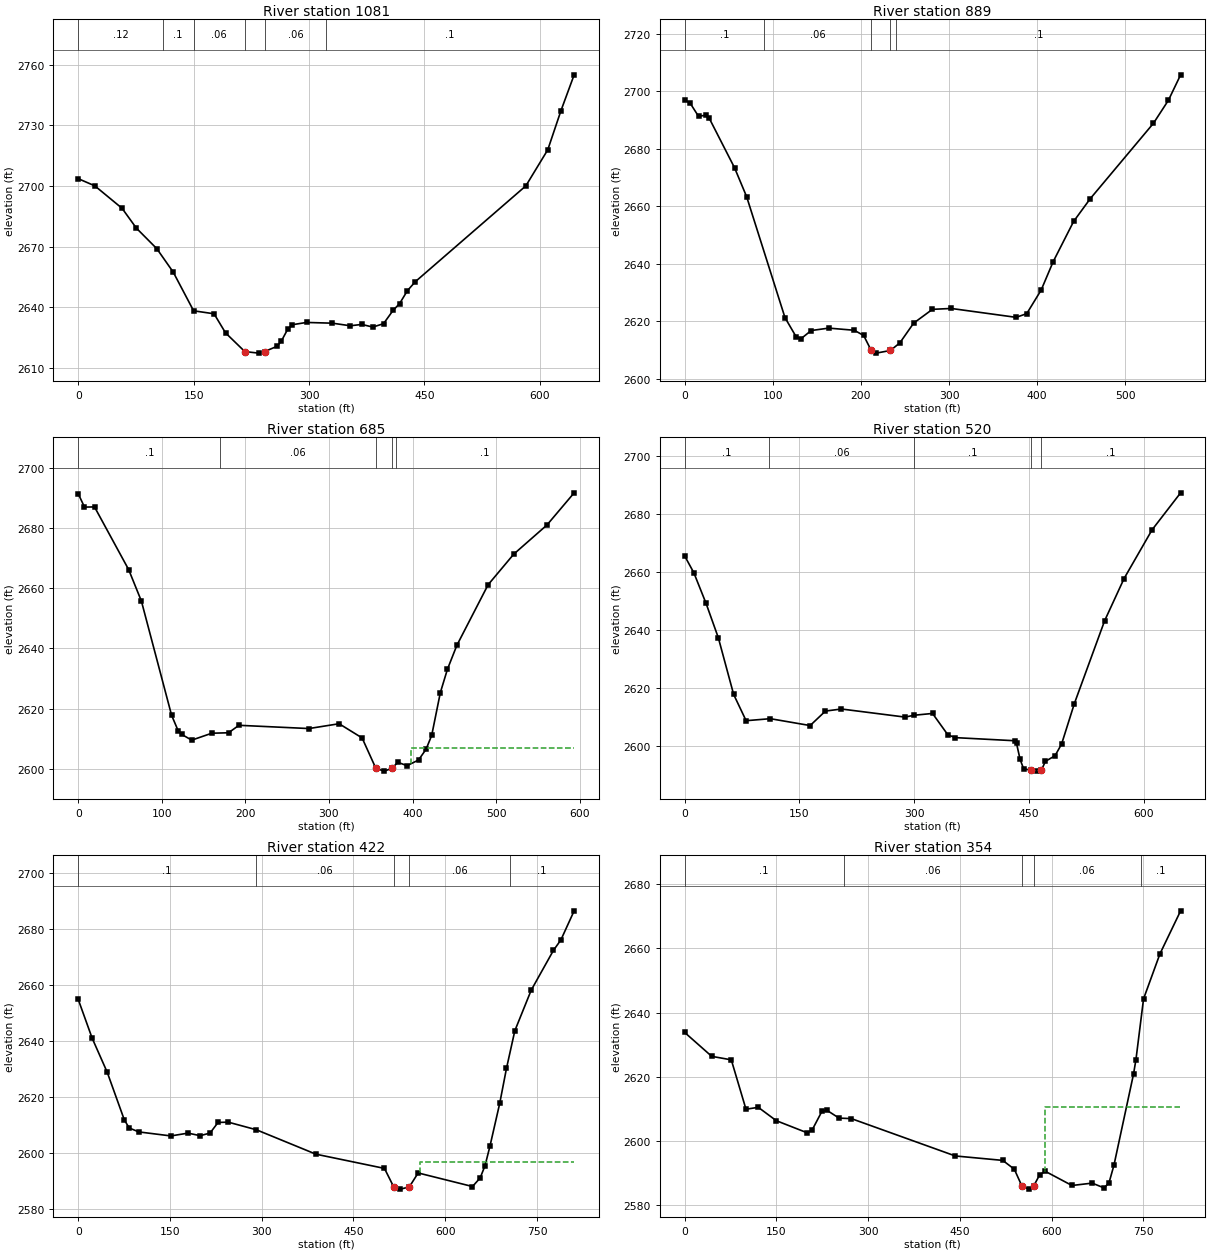
Type RM Length L Ch R = 1 ,1081    ,194.2,192.6,191.2
XS GIS Cut Line= 4
2223157.10411753561135.6373607612223019.75401652561255.755209669
2222838.73294408561374.6693990562222684.90321468561566.242181707
#Sta/Elev= 30
       0 2703.59    21.6 2700.03      57 2688.94    75.6 2679.14   102.2 2668.97
   123.5 2657.41     150 2638.29   176.6 2636.81   191.5 2627.39  216.582618.132
   234.6 2617.37  242.212618.132   258.5 2620.75   264.1 2623.36   272.7 2629.43
   278.5 2631.42   296.8 2632.53   330.5 2632.17   353.6 2630.89   368.6 2631.55
     383 2630.25   396.9 2631.92   409.5 2638.59   417.7 2641.79   427.9 2648.22
   438.2 2652.67   581.9 2700.03   610.4 2717.85   627.4 2737.03   644.7  2754.9
#Mann= 6 ,-1,0
       0     .12       0     110      .1       0     150     .06       0
  216.58    .045       0  242.21     .06       0  322.46      .1       0
Bank Sta=216.58,242.21
XS Rating Curve= 0 ,0
Exp/Cntr=0.3,0.1

Type RM Length L Ch R = 1 ,889     ,208,203.4,200.2
XS GIS Cut Line= 4
2223063.58864204561033.4739012672222945.97336589561057.916317125
2222741.84022405561234.3854860862222613.15447022561349.546679554
#Sta/Elev= 30
       0 2696.99       6 2695.98    15.7  2691.3    23.9 2691.69      28 2690.55
    56.6  2673.4    70.3 2663.35   113.8 2621.31   126.6 2614.57   132.2 2614.02
   143.5 2616.81   163.4 2617.66   192.4 2616.91   203.1 2615.09  211.652609.881
   217.3 2608.96  233.442609.882   244.1 2612.51   259.8 2619.39   281.1 2624.19
   302.5 2624.49   376.1  2621.4   388.1 2622.69   404.5 2630.91   418.1 2640.76
   441.3 2654.75   460.1 2662.64   531.9 2688.89   548.9 2696.91   562.7 2705.73
#Mann= 5 ,-1,0
       0      .1       0      90     .06       0  211.65    .045       0
  233.44     .06       0  240.13      .1       0
Bank Sta=211.65,233.44
XS Rating Curve= 0 ,0
Exp/Cntr=0.3,0.1

Type RM Length L Ch R = 1 ,685     ,165.8,165.8,165.4
XS GIS Cut Line= 4
2223043.65906416560980.6288472742222704.69581949561001.969956227
2222666.39118092561072.0860608962222551.25410941561202.213959303
#Sta/Elev= 30
       0 2691.35     7.5  2686.9    19.5 2686.96    60.4 2666.11    75.6 2655.67
   111.7 2617.77   119.7 2612.53   123.7 2611.42   135.8  2609.5   159.8  2611.8
   179.8 2611.95   192.3 2614.43     276 2613.35   312.1 2614.95   339.6 2610.24
  356.112600.116   366.1 2599.21  375.152600.117   382.4 2602.14   393.4 2601.02
   407.1  2602.9   416.1 2606.45   422.9  2611.1   433.2 2625.26   441.7 2633.04
     453    2641   490.4 2661.13   521.1 2671.29   560.7 2680.94   593.3 2691.64
#Mann= 5 ,-1,0
       0      .1       0     170     .06       0  356.11    .045       0
  375.15     .06       0  379.63      .1       0
#XS Ineff= 2 , 0
                          397.92         2606.79
Permanent Ineff=
       F       F
Bank Sta=356.11,375.15
XS Rating Curve= 0 ,0
Exp/Cntr=0.3,0.1

Type RM Length L Ch R = 1 ,520     ,91.1,97.7,104.6
XS GIS Cut Line= 4
2222984.17355771560945.3371387372222552.74551441 560943.10579032
2222523.05436586560996.643372464 2222495.8626888561149.899262508
#Sta/Elev= 30
       0 2665.48      12 2659.68      28 2649.13      44 2637.34      64 2617.87
    80.3 2608.83     112 2609.52     164 2607.16     184 2612.14   204.9 2612.85
     288 2610.07     300 2610.71     324 2611.32     344 2603.98   353.7 2603.01
   431.4 2601.94   433.8 2601.02   438.4 2595.59     443 2592.33   452.1 2591.82
   461.2 2591.49  466.272591.821   471.6 2594.86   484.1 2596.78   492.7 2600.79
   509.4 2614.72     549 2643.22   574.4 2657.72     611 2674.47   648.3 2687.18
#Mann= 5 ,-1,0
       0      .1       0     110     .06       0     300      .1       0
   452.1    .045       0  466.27      .1       0
Bank Sta=452.1,466.27
XS Rating Curve= 0 ,0
Exp/Cntr(USF)=0,0
Exp/Cntr=0.3,0.1

Type RM Length L Ch R = 1 ,422     ,66,67.9,65.4
XS GIS Cut Line= 6
2222971.53974795560929.5786276142222674.36986569560917.352885569
2222564.53253278560896.5978002352222475.91774121560912.700967332
2222346.75634316560977.8563472342222348.44777904561142.939123443
#Sta/Elev= 30
       0 2654.84    22.8    2641    47.4 2628.86    75.4 2611.85    83.4 2608.98
    99.1 2607.58   151.5 2606.15   179.5 2607.15   199.3 2606.24   215.5 2607.17
   228.6 2610.96   245.3 2611.06   291.2 2608.35   388.6 2599.64   500.6 2594.57
   515.8 2587.95   526.7 2587.18   541.2 2587.96   555.7 2592.95   644.5 2588.11
     657 2591.16     665 2595.53     673 2602.45     689 2617.74   700.1 2630.27
   713.7 2643.64   740.5 2658.13   776.9 2672.34     789 2676.04   810.7 2686.42
#Mann= 5 ,-1,0
       0      .1       0     290     .06       0   515.8    .045       0
   541.2     .06       0  705.65      .1       0
#XS Ineff= 2 , 0
                          558.27         2596.71
Permanent Ineff=
       F       F
Bank Sta=515.8,541.2
XS Rating Curve= 0 ,0
Exp/Cntr=0.3,0.1

Type RM Length L Ch R = 1 ,354     ,211,199.6,187.7
XS GIS Cut Line= 6
 2222940.3287484560892.9051383352222643.15886614 560880.67939629
2222533.32153323560859.9243109562222444.70674166560876.027478053
2222315.54534361560941.1828579552222317.23677949561106.265634164
#Sta/Elev= 30
       0  2633.8    44.2 2626.37    76.2 2625.28   100.2 2609.92   120.3 2610.51
   149.8 2606.35   200.3 2602.58   208.3 2603.44   224.3 2609.24   232.4  2609.6
   252.4 2607.15   272.4    2607   442.3 2595.38   519.9    2594   538.8 2591.27
   551.22586.045   562.9 2585.06  570.54 2586.06   580.6 2589.61   589.6 2590.59
   633.1 2586.19   666.1 2586.93   685.7 2585.43   693.7 2587.07   701.7 2592.49
   733.7 2620.84   737.7 2625.37   750.1 2644.25   776.9 2658.26   810.7 2671.64
#Mann= 5 ,-1,0
       0      .1       0     260     .06       0   551.2    .045       0
  570.54     .06       0  745.65      .1       0
#XS Ineff= 2 , 0
                          589.11         2610.48
Permanent Ineff=
       F       F
Bank Sta=551.2,570.54
XS Rating Curve= 0 ,0
Exp/Cntr=0.3,0.1