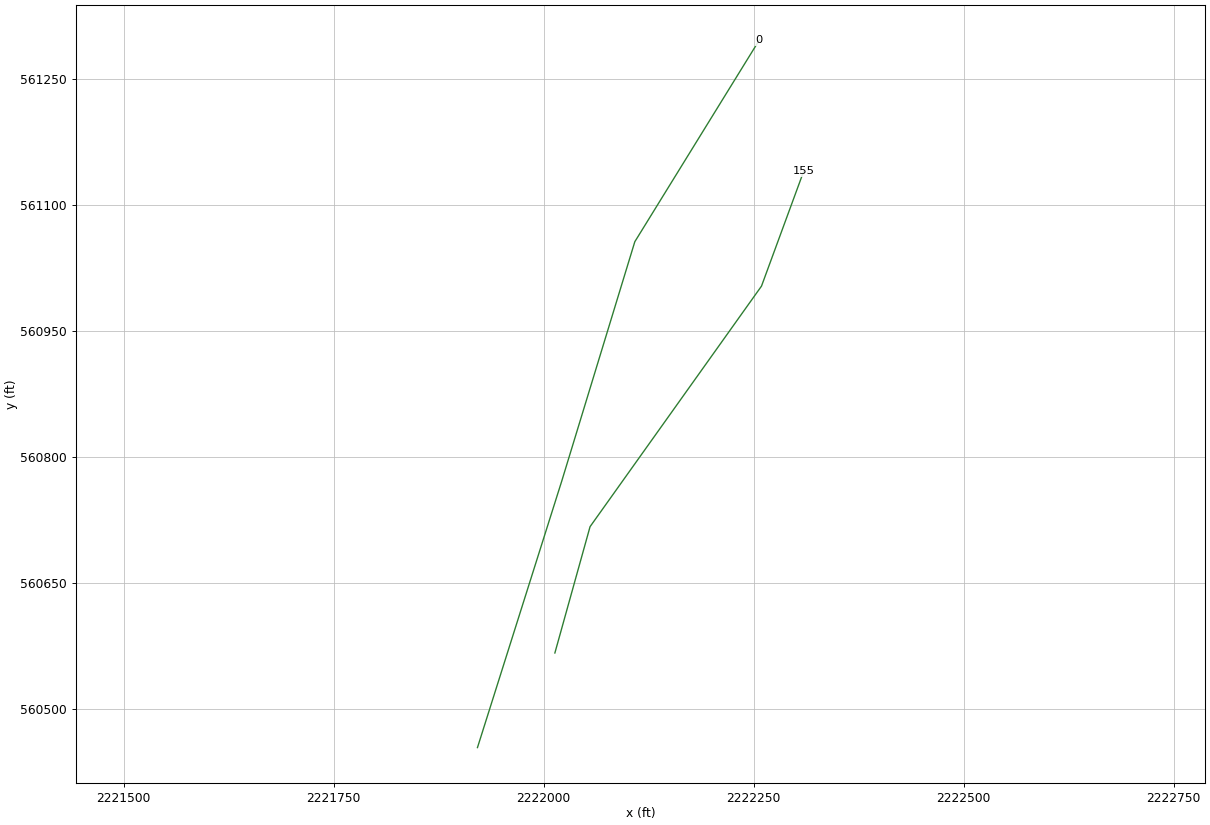
HEC-RAS study MUDLKRN.prj: MUDLKRN

--- MUDLKRN.g01 (geometry) --- (continued)

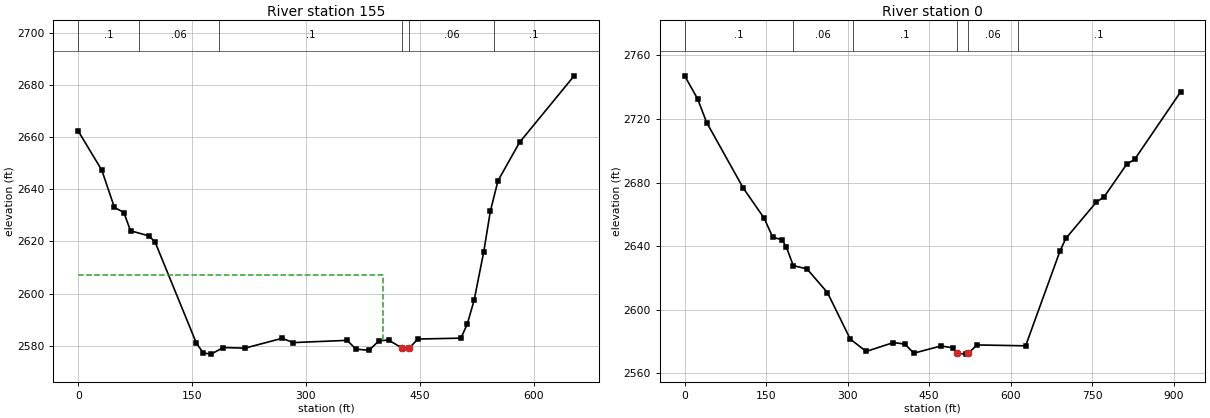
Type RM Length L Ch R = 1 ,155     ,155.3,154.6,152.9
XS GIS Cut Line= 4
 2222013.2484278560567.2154298232222055.13842976560717.584442564
2222259.22555366561003.9535981412222309.51385393561140.789157068
#Sta/Elev= 30
       0 2662.29    31.1 2647.27    47.7    2633    60.2 2631.04    68.9 2624.06
    93.4 2622.08   101.4 2619.65   155.7 2580.98   164.8 2577.22   175.2 2576.77
     191  2579.3   219.5 2579.05   268.6 2582.82   283.3 2581.19   354.4 2582.05
   365.9 2578.71   383.1  2578.2   396.3  2581.9   408.9 2582.16   426.7 2579.12
  436.482579.122   447.4 2582.55   504.3  2582.9   512.6 2588.25   521.7 2597.43
   534.4 2616.05   543.1 2631.58   553.1 2643.21   581.5 2657.92   653.5 2683.45
#Mann= 6 ,-1,0
       0      .1       0      80     .06       0  186.09      .1       0
   426.7    .045       0  436.48     .06       0  547.75      .1       0
#XS Ineff= 2 , 0
          401.81 2607.07
Permanent Ineff=
       F       F
Bank Sta=426.7,436.48
XS Rating Curve= 0 ,0
Exp/Cntr=0.3,0.1

Type RM Length L Ch R = 1 ,0       ,,,
XS GIS Cut Line= 4
2221921.10088019560454.6083333922222021.52286492560772.162083642
2222108.41507758 561056.807920222222256.68862714561296.978951876
#Sta/Elev= 30
       0 2747.18    23.7 2732.73    40.5 2717.78   107.6 2676.64   146.5 2657.45
   162.1 2645.51   178.9 2644.06   187.3 2639.29   199.9 2627.67     225 2625.66
   262.8 2610.72   304.8 2581.43   334.1 2573.65   384.3 2579.26   405.2  2578.3
   421.9 2572.59   472.1 2577.13     493 2575.92  500.62 2572.55   518.1 2571.97
   522.3 2572.53   537.9 2577.76   627.6 2577.19   691.1  2637.1   701.6 2644.81
     758 2667.76   772.1 2670.99   813.9 2691.64   828.2 2694.54   912.9 2737.05
#Mann= 6 ,-1,0
       0      .1       0     200     .06       0     310      .1       0
  500.62    .045       0   522.3     .06       0  613.05      .1       0
Bank Sta=500.62,522.3
XS Rating Curve= 0 ,0
Exp/Cntr=0.3,0.1
LCMann Table=0

Chan Stop Cuts=-1
Use User Specified Reach Order=0
Composite Channel Slope=5